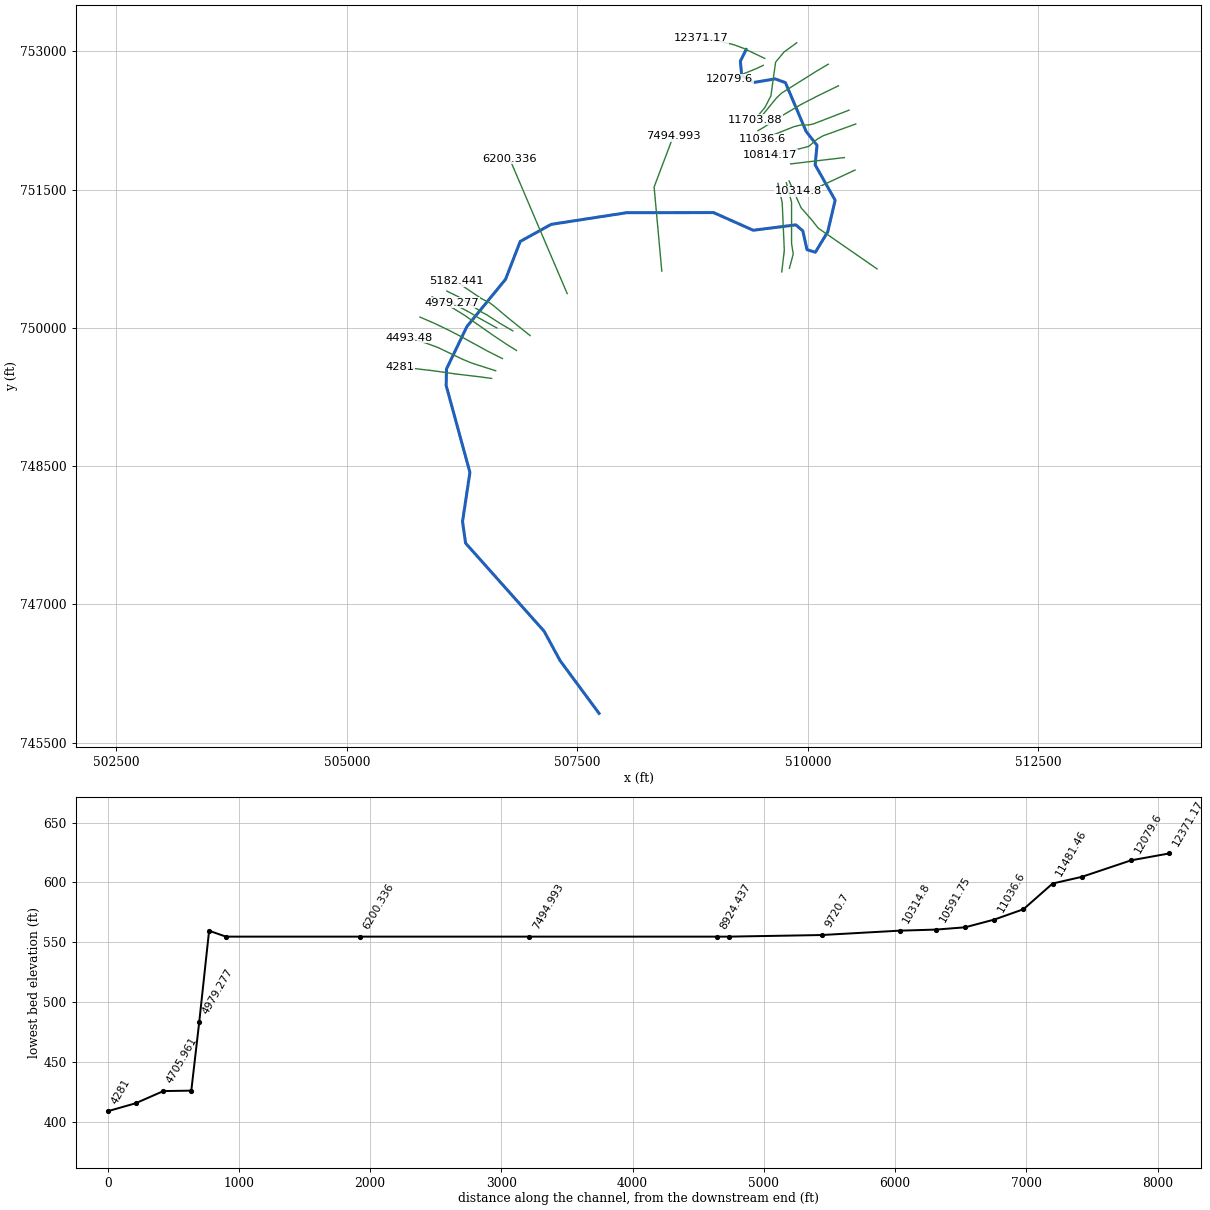
--- 1313_ras.prj (project) ---

Proj Title=1313
Current Plan=p01
Default Exp/Contr=0.3,0.1
English Units
Geom File=g01
Flow File=f01
Plan File=p01
Y Axis Title=Elevation
X Axis Title(PF)=Main Channel Distance
X Axis Title(XS)=Station
BEGIN DESCRIPTION:
RFD model 1313 exported to HEC-RAS
END DESCRIPTION:

--- 1313_ras.p01 (plan) ---

Plan Title=Plan 01
Program Version=4.10
Short Identifier=Plan 01
Geom File=g01
Flow File=f01
Subcritical Flow
Calc Critical at every XS
Secant Critical Depth

--- 1313_ras.f01 (steady flow) ---

Flow Title=Flow 01
Program Version=5.01
Number of Profiles= 6
Profile Names=10yr,25yr,50yr,100yr,100plus,500yr
River Rch & RM=1313,21,12371.17
 2335.89 3858.88 5331.54 6708.08  9793.812047.46
River Rch & RM=1313,21, 12079.6
 2338.02 3862.88 5337.49 6716.07 9805.4612061.72
River Rch & RM=1313,21,11703.88
  2343.9 3873.85 5353.82 6737.92 9837.3612100.66
River Rch & RM=1313,21,11481.46
 2346.69 3879.02 5361.47 6748.12 9852.2612118.69
River Rch & RM=1313,21,11259.03
    2348 3881.46 5365.08 6752.95 9859.3112127.22
River Rch & RM=1313,21, 11036.6
 2355.64  3895.6 5386.01 6780.85 9900.05 12176.5
River Rch & RM=1313,21,10814.17
 2360.37 3904.34 5398.92 6798.06 9925.1612206.78
River Rch & RM=1313,21,10591.75
 2362.27 3907.87 5404.15 6805.02 9935.3312219.08
River Rch & RM=1313,21, 10314.8
  2369.6 3921.43 5424.23  6831.8 9974.4312266.31
River Rch & RM=1313,21,  9720.7
 2648.46 4422.57 6154.11 7792.3711376.8613895.89
River Rch & RM=1313,21,9015.692
 2670.96 4463.92 6215.15 7873.6111495.4714035.84
River Rch & RM=1313,21,7494.993
  2790.4 4687.06 6547.58 8319.5212146.4914813.64
River Rch & RM=1313,21,6200.336
 2798.71 4702.71 6570.98 8351.03 12192.514868.82
River Rch & RM=1313,21,5182.441
  2801.2  4707.4 6578.02 8360.5112206.3414885.45
Boundary for River Rch & Prof#=1313,21,1
Up Type= 0
Dn Type= 2
Boundary for River Rch & Prof#=1313,21,2
Up Type= 0
Dn Type= 2
Boundary for River Rch & Prof#=1313,21,2
Up Type= 0
Dn Type= 2
Boundary for River Rch & Prof#=1313,21,2
Up Type= 0
Dn Type= 2
Boundary for River Rch & Prof#=1313,21,2
Up Type= 0
Dn Type= 2
Boundary for River Rch & Prof#=1313,21,2
Up Type= 0
Dn Type= 2

--- 1313_ras.g01 (geometry) ---

Geom Title=1313
Program Version=4.10

River Reach=1313,21
Reach XY= 30
509330.999901497753020.066174454 509268.47861478752893.307671212
  509282.8235284752736.219258632509411.178391321752662.044454751
509645.468481341752701.106546787509756.959759171752660.673468739
509982.063214285752130.379199076510099.977500377751980.300237123
510079.566672128751768.834595126510296.547725961751384.741701952
510215.637570358751041.190962546510082.328690984 750820.86918025
509991.600649657750847.877151238509945.451966873751052.615584598
509869.760710208751117.499764645509408.241805669751058.984803404
508977.388168479751250.686131536508037.404494045751249.730678728
507216.344766869751123.273191697506879.980048583750937.652770599
506721.177885431750527.809427536506301.278912961750013.718302291
506080.374591766 749554.81366017506076.636752426749374.530151632
506334.273893146748432.152420468506254.119726745 747897.96146613
506287.504757851747664.314887029507139.285155324746709.267900799
507312.567335694746390.009043152507735.230025577745817.918665918

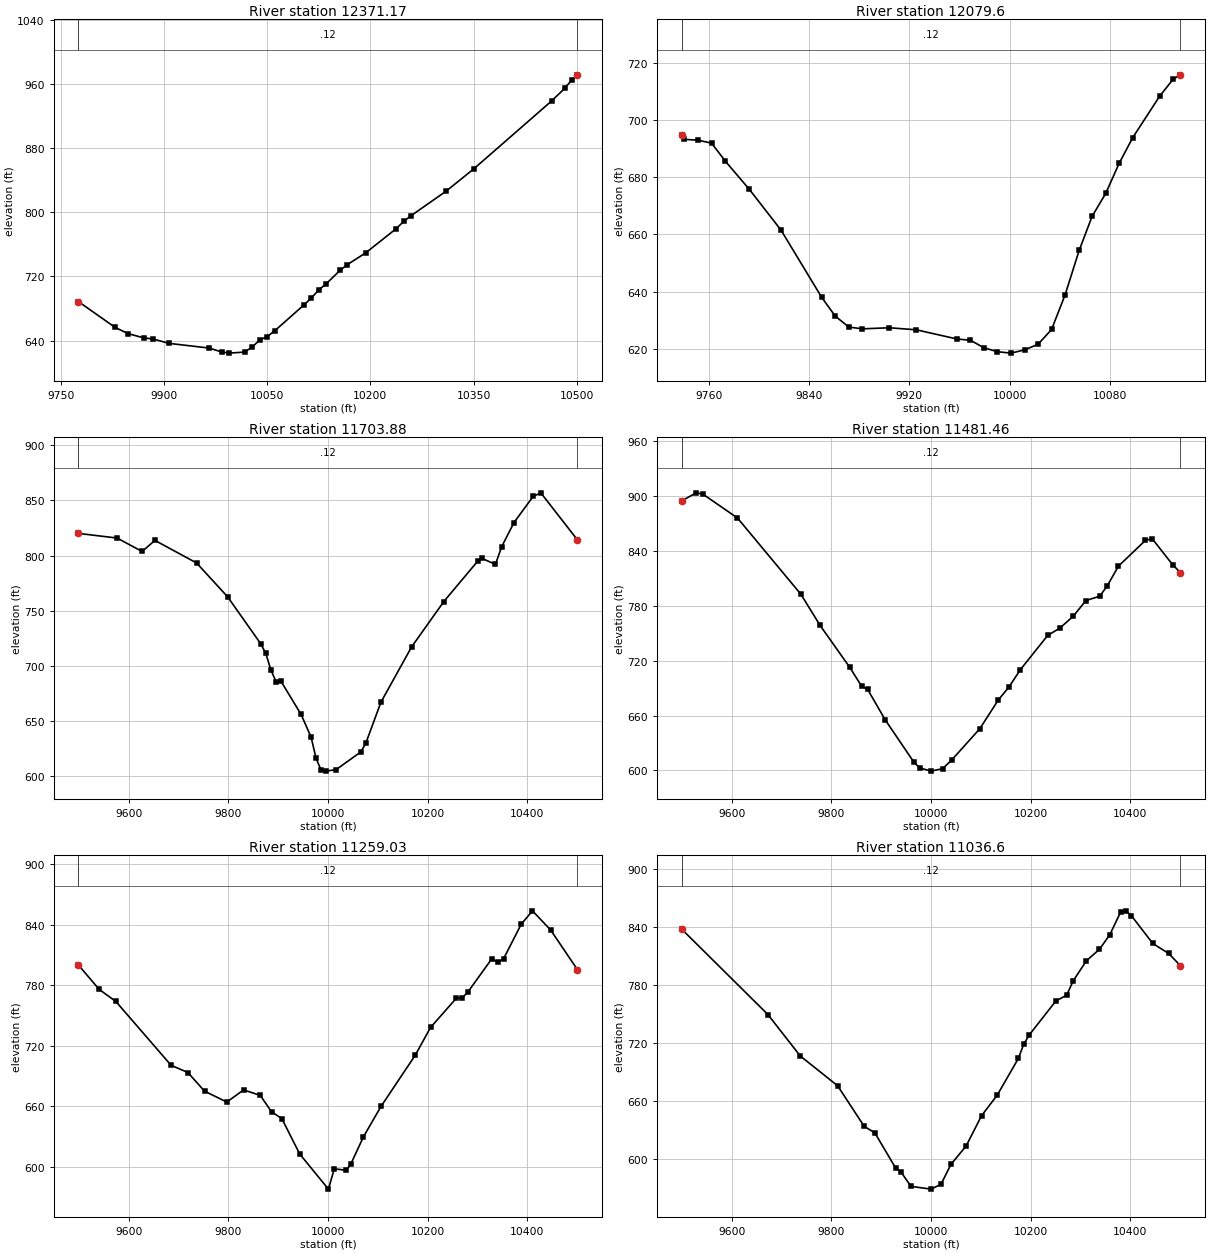
Type RM Length L Ch R = 1 ,12371.17,291.563500,291.563500,291.563500
XS GIS Cut Line= 6
509532.841178358752923.181864634509299.500303864753034.213296354
509206.183759749753069.113732517509101.062657237753096.425385505
509033.537476569753110.074381307508846.818560749753141.057621896
#Sta/Elev= 30
9775.977688.5348 9829.26 656.342 9848.25648.50859870.965643.28619884.947641.8106
9907.222636.46959965.758630.58349983.966625.71999995.042624.244910017.27625.5721
10028.38631.900710039.36640.668210050.18645.0058   10061652.0211 10103.7684.5319
10114.28692.978510124.85703.0201 10135.4 710.44310156.18727.723710166.57734.7381
10193.37749.525110236.63     77910248.99789.033910259.19795.8789 10310.2826.5149
10350.76854.654310463.96939.535810482.53 954.91610492.67965.401610500.96971.7763
#Mann= 3 , 0 , 0
9775.977    0.12       09775.977    0.12       010500.96    0.12       0
#XS Ineff= 2 , 0
       0                               0
Bank Sta=9775.977,10500.96
Exp/Cntr=0.3,0.1

Type RM Length L Ch R = 1 , 12079.6,375.718600,375.718600,375.718600
XS GIS Cut Line= 3
509516.615971953752848.296296522509441.420320749  752812.4388078
509149.676688135752694.780881882
#Sta/Elev= 30
9738.429694.73249740.219693.21179751.298692.94959762.377691.90329773.455685.5482
9792.553675.7127 9817.77661.48919850.224637.96479861.007631.41889871.789 627.605
9882.572 626.9669904.137627.34859925.702626.6335 9958.05623.41989968.833 622.976
9979.615620.34679990.398618.973610001.18618.478910011.96619.610110022.75 621.566
10033.53 626.74610044.31638.848110055.52654.387810065.88666.340210076.66 674.294
10087.44684.862110098.22693.804210119.79708.367310130.57714.289210136.31715.7787
#Mann= 3 , 0 , 0
9738.429    0.12       09738.429    0.12       010136.31    0.12       0
#XS Ineff= 2 , 0
       0                               0
Bank Sta=9738.429,10136.31
Exp/Cntr=0.3,0.1

Type RM Length L Ch R = 1 ,11703.88,222.427400,222.427400,222.427400
XS GIS Cut Line= 6
509879.641822445753092.687972792 509740.58784057752991.289270871
509650.778353932752882.718837476509599.517221628752516.666243061
509534.035433586752390.013870523509424.095188732752259.695407761
#Sta/Elev= 30
9499.171820.16839576.758815.95699626.929803.77729652.514813.84199736.306793.3602
9798.558762.68219864.751720.31419875.156711.46139885.517696.26069895.695685.9153
9905.873686.0215 9946.06656.08749966.098 635.5559976.106616.36529986.113605.6834
 9996.12604.691710016.17605.990110066.23622.180910076.23630.288310106.35667.1646
10168.02717.3532 10232.6 758.40610300.43794.901410309.56797.481210336.23792.0546
10348.61807.936610373.37 829.94510411.85 853.64710427.36 856.94910500.86814.2843
#Mann= 3 , 0 , 0
9499.171    0.12       09499.171    0.12       010500.86    0.12       0
#XS Ineff= 2 , 0
       0                               0
Bank Sta=9499.171,10500.86
Exp/Cntr=0.3,0.1

Type RM Length L Ch R = 1 ,11481.46,222.427300,222.427300,222.427300
XS GIS Cut Line= 6
510221.717934333752860.172797838510095.663294934752785.819184538
509713.823146462752545.918893292509660.695650659752494.931987242
509515.181341886752317.029464132509443.556358015752246.151362032
#Sta/Elev= 30
9499.046894.92679528.911903.74819541.676902.40719611.336876.22629738.717792.7569
9777.339758.57459836.954712.6355  9860.8692.00629872.723688.62829907.746655.5266
9965.524609.0431 9977.08602.689210000.24 599.14310023.34601.844310041.52611.3001
10097.92645.511310135.22677.107810156.24691.027510179.33710.111810234.23747.6288
10259.26755.930510285.49768.615210311.13785.872110338.87790.607110354.25802.2545
10376.43823.580910430.35  851.6210443.87853.698210485.15825.113610500.89816.4288
#Mann= 3 , 0 , 0
9499.046    0.12       09499.046    0.12       010500.89    0.12       0
#XS Ineff= 2 , 0
       0                               0
Bank Sta=9499.046,10500.89
Exp/Cntr=0.3,0.1

Type RM Length L Ch R = 1 ,11259.03,222.427400,222.427400,222.427400
XS GIS Cut Line= 6
510332.566529906752626.256738925510112.393043703752519.293246687
 509923.88749177752422.202822149509709.200520703752295.362625086
509512.209758124752169.855333111509458.442682861752138.686726084
#Sta/Elev= 30
9499.019799.78059540.785775.59919574.137763.70229684.971700.44489718.667693.3014
9752.083674.8452  9796.9663.98519830.512676.05549864.124670.59119886.614654.3676
 9907.35647.60049943.261612.5268 10000.9577.687610012.72597.821510036.36596.4026
10045.48602.117810071.26629.576910106.55659.706110175.39710.553910205.92737.9264
10257.65 766.89210269.51 767.19610281.36773.356910328.79805.943810340.65802.6713
10352.51805.948810388.08840.339310410.63853.595310447.15834.587310500.96795.2881
#Mann= 3 , 0 , 0
9499.019    0.12       09499.019    0.12       010500.96    0.12       0
#XS Ineff= 2 , 0
       0                               0
Bank Sta=9499.019,10500.96
Exp/Cntr=0.3,0.1

Type RM Length L Ch R = 1 , 11036.6,222.427300,222.427300,222.427300
XS GIS Cut Line= 6
510446.673794585752361.833124244510058.955973761752211.886423874
510005.760344185752201.088954824509925.087612944752201.473655847
509849.404523311752182.413808384509502.665029919 752045.71468104
#Sta/Elev= 30
9499.088838.35179672.474749.82219737.569 706.8799812.511676.06289866.021633.9412
9887.226627.37839929.229590.66059939.539586.99459959.869571.92589999.966569.0735
10020.01574.014810040.06594.6999 10070.5613.683410101.42644.998810132.83666.2545
10175.48 704.38910186.14 718.98210196.81728.343110250.75763.841710272.38769.8169
10285.76784.891810312.03805.4139 10338.3817.383510358.89832.267110380.52 855.555
10390.84857.133210402.15852.245610445.31 823.34310477.18813.019210500.91800.3021
#Mann= 3 , 0 , 0
9499.088    0.12       09499.088    0.12       010500.91    0.12       0
#XS Ineff= 2 , 0
       0                               0
Bank Sta=9499.088,10500.91
Exp/Cntr=0.3,0.1

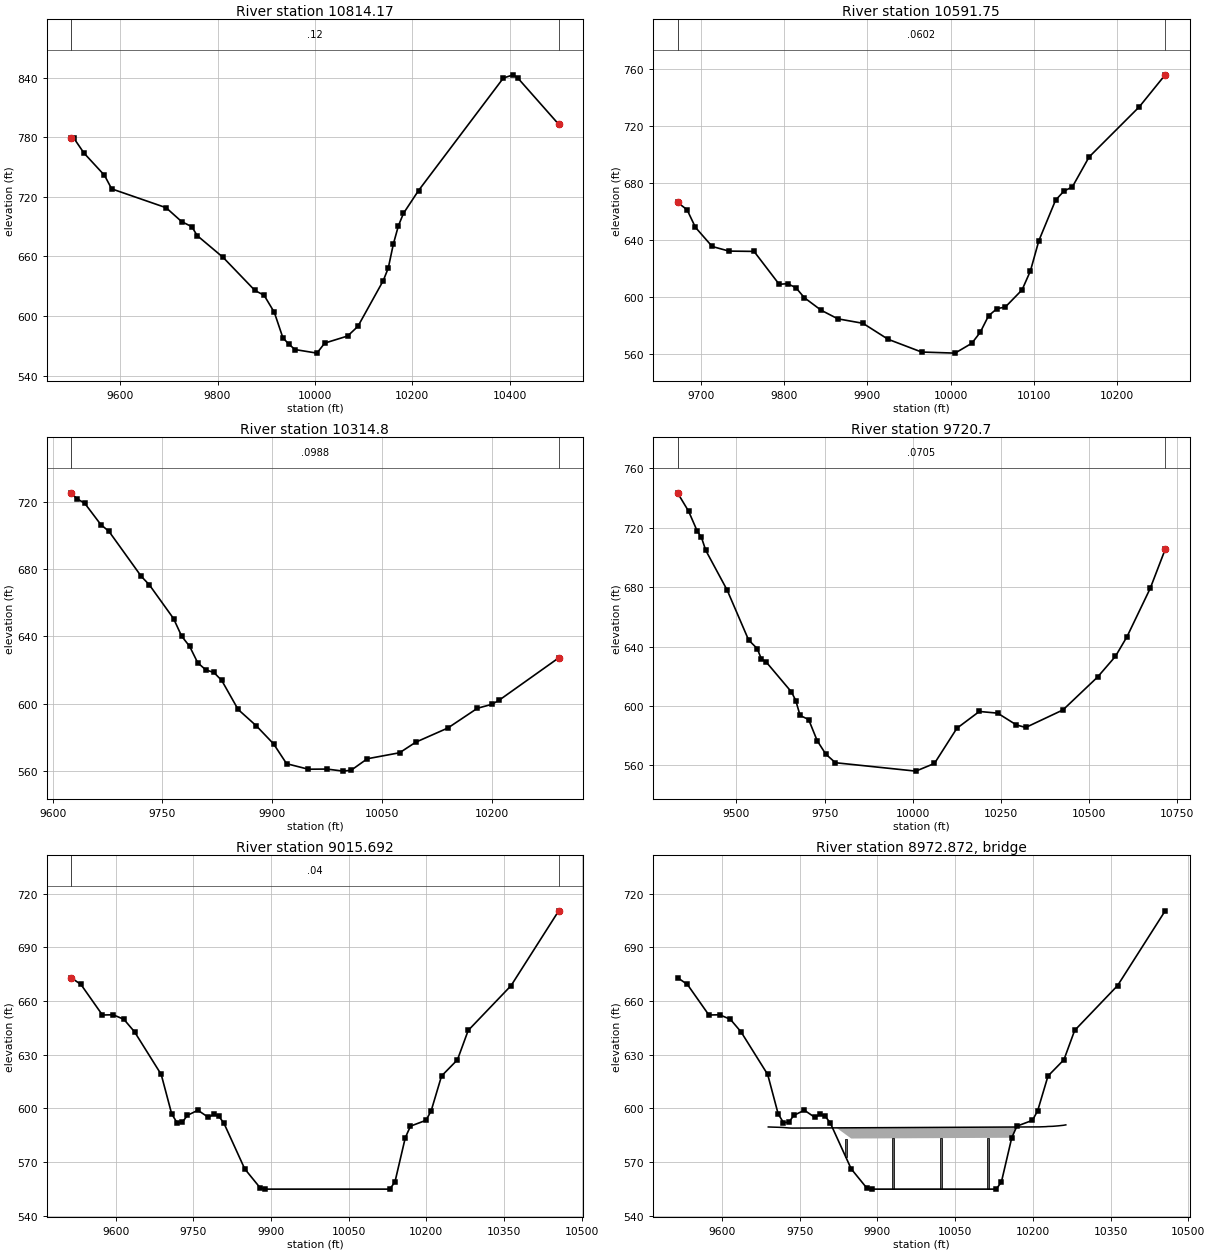
Type RM Length L Ch R = 1 ,10814.17,222.427400,222.427400,222.427400
XS GIS Cut Line= 6
510520.116514657752211.559514673510162.117672478752082.328868578
510103.546337396752048.001677603510010.015649103751968.869255987
509761.452263515751903.739981954 509592.28983841751878.854683513
#Sta/Elev= 30
9499.118779.56639504.516779.20919525.614764.00899567.811741.57489582.518727.9663
9694.402708.9814 9726.05695.08499747.372689.79089758.055680.99119811.473658.9751
9876.777625.70699895.688620.84049916.696603.62199934.224578.10789946.151571.7907
9959.276566.211210004.23562.626210020.16 572.706 10067.3579.858310088.33589.5567
10140.34 635.50310150.74648.262210161.15672.379410171.55690.823210181.95703.2933
10212.87726.250210387.22839.555810407.53842.734310417.64839.048310500.86792.9015
#Mann= 3 , 0 , 0
9499.118    0.12       09499.118    0.12       010500.86    0.12       0
#XS Ineff= 2 , 0
       0                               0
Bank Sta=9499.118,10500.86
Exp/Cntr=0.3,0.1

Type RM Length L Ch R = 1 ,10591.75,276.945100,276.945100,276.945100
XS GIS Cut Line= 2
 510396.37876147751847.652268365509814.142019153751778.761661455
#Sta/Elev= 30
9671.744666.36129683.202661.22739693.272648.86429713.412635.44759733.551632.2241
 9763.76631.9984 9793.97608.94949804.039609.38459814.109606.55279824.179599.5845
9844.318  590.829864.458584.76079894.667581.62259924.876570.43899965.155561.4977
10005.43560.725410025.57567.639510035.64575.264810045.71586.909110055.78  591.87
10065.85593.021710085.99605.072510096.06618.417110106.13639.479910126.27667.9174
10136.34674.286110146.41677.183110166.55698.163710226.97733.358210258.04755.7317
#Mann= 3 , 0 , 0
9671.744  0.0602       09671.744  0.0602       010258.04  0.0602       0
#XS Ineff= 2 , 0
       0                               0
Bank Sta=9671.744,10258.04
Exp/Cntr=0.3,0.1

Type RM Length L Ch R = 1 , 10314.8,594.101300,594.101300,594.101300
XS GIS Cut Line= 3
510511.937198907751712.093332186510045.258893967751494.310123205
509894.144014299751483.198734984
#Sta/Elev= 30
9625.053725.25079632.708721.85769643.743719.03249665.814706.32749676.849 702.355
9720.991675.62539732.026 670.5679765.132650.52149776.167640.09689787.202633.9386
9798.238624.18639809.273620.02319820.308618.45629831.003613.72559853.414596.4679
9878.297586.74629901.944575.98099919.626564.25419949.238560.97269974.802561.0584
9996.873559.832510007.91560.379710029.98567.189210074.12  570.7610096.19577.0368
10140.05585.464110180.41597.198510200.47599.578410210.49602.106210291.57627.1561
#Mann= 3 , 0 , 0
9625.053  0.0988       09625.053  0.0988       010291.57  0.0988       0
#XS Ineff= 2 , 0
       0                               0
Bank Sta=9625.053,10291.57
Exp/Cntr=0.3,0.1

Type RM Length L Ch R = 1 ,  9720.7,705.008300,705.008300,705.008300
XS GIS Cut Line= 5
510750.823869854750639.902723834510113.804639101751081.171253473
510044.130660713751169.093178555509926.348459214751303.464422554
509796.953927934751593.772665724
#Sta/Elev= 30
9332.745743.4414 9364.16731.07949388.489717.78069400.654713.42899412.819704.7503
9473.644677.96119534.468644.41269558.798 638.6379570.963 631.5169583.128629.9501
9656.117609.42319668.282603.65999680.447593.64769704.776590.90579729.106576.6304
9753.436567.6263 9780.73 561.845 10008.9556.190810061.71561.363410125.32585.0071
10189.11596.335710241.01595.200110294.39587.247210320.79585.580110426.41597.3788
10524.67619.521110575.39633.464710608.24646.739310673.93679.174410716.38705.3912
#Mann= 3 , 0 , 0
9332.745  0.0705       09332.745  0.0705       010716.38  0.0705       0
#XS Ineff= 2 , 0
       0                               0
Bank Sta=9332.745,10716.38
Exp/Cntr=0.3,0.1

Type RM Length L Ch R = 1 ,9015.692,91.255000,91.255000,91.255000
XS GIS Cut Line= 5
509800.271736443750646.538340822509841.744342595750800.816435769
509823.496395886750918.598637298509823.496395886751363.184975415
509767.093651503751573.865814775
#Sta/Elev= 30
9513.891 673.0539533.008669.22239574.428652.16789595.138652.29189615.848649.7808
9636.558642.72519687.999618.91979708.238596.87199718.357592.06999728.476592.1534
9738.596596.08839758.834 598.9529779.073594.95299789.192596.69149799.235 595.604
9809.235591.58339849.235566.17599879.235555.49979889.235554.854510129.24554.8545
10139.24558.818310159.24583.562510169.24590.052210199.24593.314710209.24598.6299
10229.24618.0723   10260627.163710280.71643.551710363.52668.588410455.52710.3894
#Mann= 3 , 0 , 0
9513.891    0.04       09513.891    0.04       010455.52    0.04       0
#XS Ineff= 2 , 0
       0                               0
Bank Sta=9513.891,10455.52
Exp/Cntr=0.3,0.1

Type RM Length L Ch R = 3 ,8972.872,,,
BEGIN DESCRIPTION:
END DESCRIPTION:
Bridge Culvert--1,0,-1,-1, 0
Deck Dist Width WeirC Skew NumUp NumDn MinLoCord MaxHiCord MaxSubmerge Is_Ogee
32.340150,26.574700,2.6,0, 18, 18, , , 0.95, 0, 0,0,,
 9689.15 9697.79 9707.81 9717.84 9727.86 9734.67 9749.02 9749.0210203.0910203.09
10212.9610218.2910225.3910228.5310238.7610249.0010259.2310263.64
  589.60  589.51  589.42  589.30  589.07  588.97  588.99  588.99  589.62  589.62
  589.64  589.70  589.77  589.86  589.97  590.22  590.54  590.77
 -410.40 -410.49 -410.58 -410.70 -410.93 -411.03 -411.01  582.99  583.62 -410.38
 -410.36 -410.30 -410.23 -410.14 -410.03 -409.78 -409.46 -409.23
 9689.15 9697.79 9707.81 9717.84 9727.86 9734.67 9747.13 9747.1310201.1910201.19
10212.9610218.2910225.3910228.5310238.7610249.0010259.2310263.64
  589.60  589.51  589.42  589.30  589.07  588.97  588.99  588.99  589.62  589.62
  589.64  589.70  589.77  589.86  589.97  590.22  590.54  590.77
 -410.40 -410.49 -410.58 -410.70 -410.93 -411.03 -411.01  582.99  583.62 -410.38
 -410.36 -410.30 -410.23 -410.14 -410.03 -409.78 -409.46 -409.23
Pier Skew, UpSta & Num, DnSta & Num=  ,9838.63, 2 ,9836.74, 2 , 0 , 0 , 0 ,,
    4.00    4.00
 -410.88  589.12
    4.00    4.00
 -410.89  589.11
Pier Skew, UpSta & Num, DnSta & Num=  ,9930.25, 2 ,9928.35, 2 , 0 , 0 , 0 ,,
    4.00    4.00
 -410.76  589.24
    4.00    4.00
 -410.76  589.24
Pier Skew, UpSta & Num, DnSta & Num=  ,10021.86, 2 ,10019.97, 2 , 0 , 0 , 0 ,,
    4.00    4.00
 -410.63  589.37
    4.00    4.00
 -410.63  589.37
Pier Skew, UpSta & Num, DnSta & Num=  ,10113.47, 2 ,10111.58, 2 , 0 , 0 , 0 ,,
    4.00    4.00
 -410.50  589.50
    4.00    4.00
 -410.50  589.50
BR Coef=-1 , 0 , 0 ,, 0 ,,,0.8,0,1,0,
WSPro=,,,, 1 ,,,, 0 ,,,, 0 ,,,,-1 ,-1 ,-1 , 0 , 0 , 0 , 0 , 0
BC Design=,, 0 ,, 0 ,,,,,,

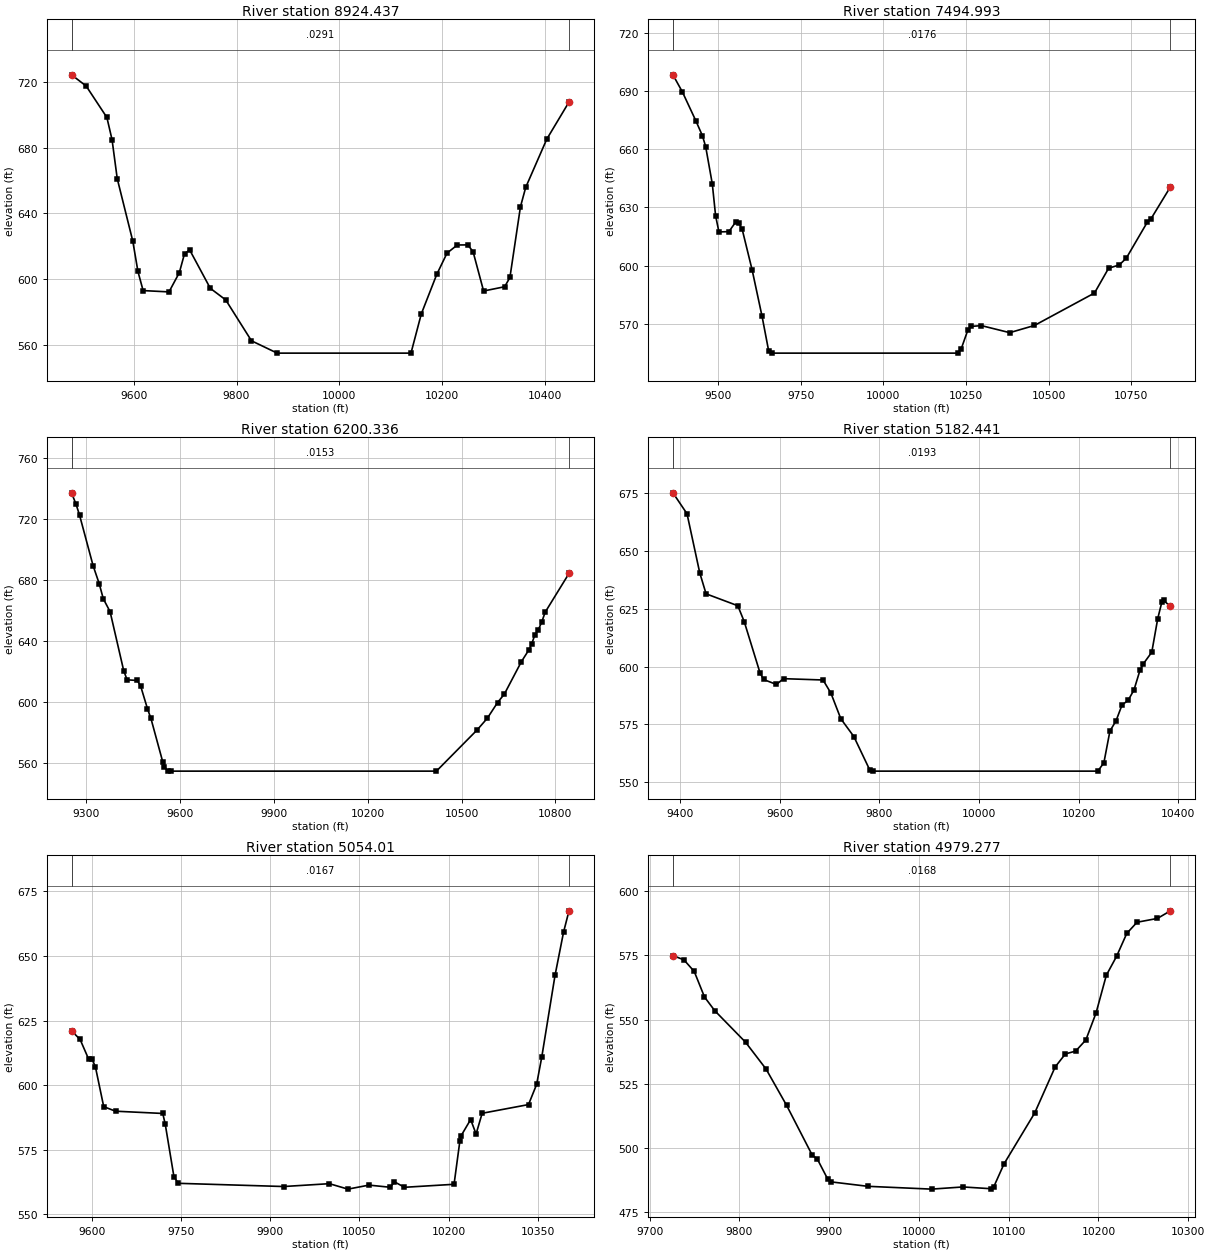
Type RM Length L Ch R = 1 ,8924.437,1429.443700,1429.443700,1429.443700
XS GIS Cut Line= 4
509717.326524109750606.724638894509744.943390369750840.677289948
509722.303236842751356.549358442509675.853917927751567.230197772
#Sta/Elev= 30
9479.024724.34169507.495717.51089547.773698.38339557.843 684.8149567.912661.1307
 9598.12623.1351 9608.19604.58639618.259592.94029668.606592.14169688.745603.8937
9698.815615.45139708.884617.67479748.957594.33129778.985587.24899829.034562.3672
9879.082554.854510139.33554.854510159.35 578.70310189.38602.7399 10209.4615.7521
10229.42620.709810249.86620.7757 10260.1616.630910280.58 592.68710321.54595.2867
10331.78600.916210352.26643.9745 10362.5655.789910403.47685.173210446.71707.7751
#Mann= 3 , 0 , 0
9479.024  0.0291       09479.024  0.0291       010446.71  0.0291       0
#XS Ineff= 2 , 0
       0                               0
Bank Sta=9479.024,10446.71
Exp/Cntr=0.3,0.1

Type RM Length L Ch R = 1 ,7494.993,1294.657400,1294.657400,1294.657400
XS GIS Cut Line= 3
508415.756512076750616.340023503508332.423178732751527.798356846
508540.756512076752079.881690159
#Sta/Elev= 30
9363.323698.35459392.102  689.499432.269674.80289452.353667.04239462.394661.3404
9482.478642.0866 9492.52625.58679502.561617.34219532.686617.5124 9552.77622.3352
9562.811 621.8299572.853618.72699602.978597.75929633.103573.76489653.187555.8585
9663.229554.854510225.56554.854510235.61557.038410255.69566.717210265.73568.6395
10296.97569.032110382.47565.406910457.29569.122410638.99585.847410681.75598.6396
10713.81600.309210735.19603.806810799.32 622.52610810.01624.124410868.67640.5515
#Mann= 3 , 0 , 0
9363.323  0.0176       09363.323  0.0176       010868.67  0.0176       0
#XS Ineff= 2 , 0
       0                               0
Bank Sta=9363.323,10868.67
Exp/Cntr=0.3,0.1

Type RM Length L Ch R = 1 ,6200.336,1017.894500,1017.894500,1017.894500
XS GIS Cut Line= 2
507389.714845419750371.548356846506764.714845419751835.090023503
#Sta/Elev= 30
9252.279737.11059266.906 729.487 9277.78722.60699321.274689.38339340.672677.7079
9353.895 667.7159375.643659.25289419.138620.65979430.011614.64119462.632614.2227
9473.506  610.459495.253595.66499506.127589.42929544.372560.67249549.622557.7639
9560.495  554.979569.835554.854510419.52554.8545   10550581.874110582.62589.5539
10615.24599.793610636.99605.344310691.36626.541110715.65634.354510723.98637.9304
10734.85  644.3110745.73647.4751 10756.6 652.59210767.47658.940410843.69684.3074
#Mann= 3 , 0 , 0
9252.279  0.0153       09252.279  0.0153       010843.69  0.0153       0
#XS Ineff= 2 , 0
       0                               0
Bank Sta=9252.279,10843.69
Exp/Cntr=0.3,0.1

Type RM Length L Ch R = 1 ,5182.441,128.431400,128.431400,128.431400
XS GIS Cut Line= 6
506987.215213652 749916.34908146506743.140187322750112.546065327
506594.185261394750238.065390653 506549.20817398750271.509492622
506456.254861222750319.356117507506183.549244723750504.261882465
#Sta/Elev= 30
9385.978674.99089414.272665.94389439.745640.49229452.481631.39219516.165626.2504
9529.063619.37459560.533597.40579567.759594.41099593.555592.28319608.031594.7664
9687.194594.1975 9702.95588.53599722.864577.45449749.018569.77749780.543555.5345
9788.249554.854510238.52554.854510250.68558.460510262.84572.1749   10275576.5267
10287.16583.436210299.15585.345410311.06589.887710322.98598.298610330.02601.2344
 10346.8606.191210358.72620.679810366.82 627.67210370.63628.551610384.15625.9433
#Mann= 3 , 0 , 0
9385.978  0.0193       09385.978  0.0193       010384.15  0.0193       0
#XS Ineff= 2 , 0
       0                               0
Bank Sta=9385.978,10384.15
Exp/Cntr=0.3,0.1

Type RM Length L Ch R = 1 , 5054.01,74.732700,74.732700,74.732700
XS GIS Cut Line= 6
506799.720884055  749967.7592365506663.443335414750047.120867774
506515.942929804750142.515151829506463.035175622750170.572294205
506224.148649156750330.097189382506083.862937301 750399.03759636
#Sta/Elev= 30
9565.749621.04969580.138617.71059594.356610.17379600.009610.26239605.929607.0714
 9619.88591.69089639.751589.93039719.236589.05719723.451584.82479738.021564.5784
9745.377 562.0159922.817560.77239999.566561.874810030.73559.765310066.14561.3186
   10102560.482910108.98 562.59110125.92560.4754 10209.3 561.63710219.16578.5291
10221.31580.495610237.19586.700810246.37 581.10910256.57589.125910334.56592.4926
10348.18600.290610356.85610.875410379.13642.462610393.53659.264210402.68667.4958
#Mann= 3 , 0 , 0
9565.749  0.0167       09565.749  0.0167       010402.68  0.0167       0
#XS Ineff= 2 , 0
       0                               0
Bank Sta=9565.749,10402.68
Exp/Cntr=0.3,0.1

Type RM Length L Ch R = 1 ,4979.277,60.835900,60.835900,60.835900
XS GIS Cut Line= 5
506625.766601384 749999.82454206506431.771502733750107.243315712
506340.385381818750162.555967808506269.841709614750201.034334466
506142.382119954750270.776374072
#Sta/Elev= 30
9725.924574.8831 9738.23573.17879749.661568.68599761.092558.75929772.523553.4373
9806.815541.19029829.676530.75519852.537516.66149881.112497.29869886.829495.7428
 9898.26488.05449901.755486.91389943.042485.174710014.03484.0824 10049.1484.9282
10080.48484.234110083.41485.0215 10094.8493.899310128.97513.682510151.77531.5745
10163.17536.641110174.57537.727210185.97542.065110197.37552.609510208.76567.2092
10220.16574.546410231.56583.479210242.96587.810110265.76589.305910280.14592.2532
#Mann= 3 , 0 , 0
9725.924  0.0168       09725.924  0.0168       010280.14  0.0168       0
#XS Ineff= 2 , 0
       0                               0
Bank Sta=9725.924,10280.14
Exp/Cntr=0.3,0.1

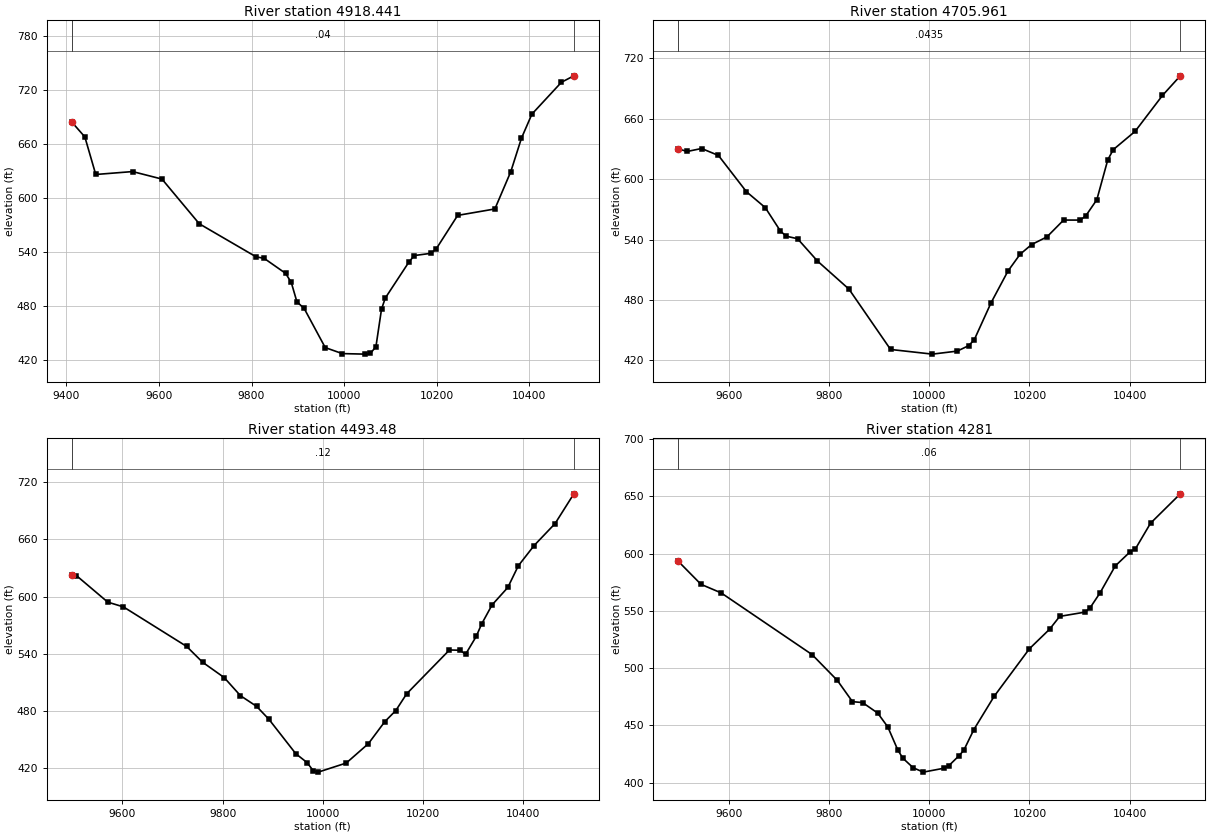
Type RM Length L Ch R = 1 ,4918.441,212.480400,212.480400,212.480400
XS GIS Cut Line= 6
506839.027576284749754.930405041 506750.20457973749810.074368632
506575.227268699749926.821292431506280.376025888750133.677185989
506158.576807971750209.317771254505924.657220737750337.420355918
#Sta/Elev= 30
9411.464684.15389439.745667.60899463.286625.90549542.904629.1426 9606.42620.8118
9687.045571.1936 9809.84534.47679827.167532.83099873.582516.15119885.827506.1441
9898.073484.55939913.801477.13329959.299433.72689996.034 427.04910044.69426.4536
10056.78427.185410068.87434.701110080.96476.380910089.05488.664310139.96528.5123
10151.73535.896810187.05538.331110198.82543.014610245.52580.493310325.97587.6397
10360.44 629.15910383.43666.219510406.01692.939310469.84728.301610496.66 735.447
#Mann= 3 , 0 , 0
9411.464    0.04       09411.464    0.04       010496.66    0.04       0
#XS Ineff= 2 , 0
       0                               0
Bank Sta=9411.464,10496.66
Exp/Cntr=0.3,0.1

Type RM Length L Ch R = 1 ,4705.961,212.480300,212.480300,212.480300
XS GIS Cut Line= 6
506686.682570145749666.974943235506534.658039688 749743.27159352
506219.169804471749915.770647436506115.077231168749969.598190895
505962.057710395750043.468352198 505792.30078523750117.486594748
#Sta/Elev= 30
9499.016630.13929516.907627.57379545.653630.50819579.219623.60749635.163587.5271
9672.713571.73319702.918548.46949714.316543.36899737.114540.82799776.891518.6273
9839.701490.72739922.741430.7373 10006.2426.098910055.89429.110210078.41434.4737
10089.66440.266110123.44477.277710157.06508.704110181.29525.4067 10204.3535.0481
10234.79542.6287 10268.1559.372110301.41559.341910312.52 563.70810334.39579.6109
10356.21619.226210367.12 629.35310410.76647.5479 10465.3683.201410500.98702.7536
#Mann= 3 , 0 , 0
9499.016  0.0435       09499.016  0.0435       010500.98  0.0435       0
#XS Ineff= 2 , 0
       0                               0
Bank Sta=9499.016,10500.98
Exp/Cntr=0.3,0.1

Type RM Length L Ch R = 1 , 4493.48,212.480400,212.480400,212.480400
XS GIS Cut Line= 6
506613.709276631749535.066670413506352.151123798749618.681109838
506250.979359079 749661.02380117505990.493412456749785.807411905
505858.827161018749834.483260472505679.364893069749891.326978489
#Sta/Elev= 30
9499.056 622.9299508.153622.16679570.823594.25669602.158589.24989728.325547.7571
9760.104531.19119803.148515.1208 9835.67496.09239867.787484.93189892.243471.4697
9946.045435.2527 9968.43425.9779  9981.3417.16039990.815415.893910046.85 425.449
   10091445.788110123.74468.882710145.57480.4375 10167.4498.106210252.81544.0703
10274.13543.725910284.79539.429210306.12558.239710316.71 571.05510337.69591.2738
10369.16609.601410390.14632.363110421.61653.589810463.57676.707210500.95707.8616
#Mann= 3 , 0 , 0
9499.056    0.12       09499.056    0.12       010500.95    0.12       0
#XS Ineff= 2 , 0
       0                               0
Bank Sta=9499.056,10500.95
Exp/Cntr=0.3,0.1

Type RM Length L Ch R = 1 ,    4281,0.000000,0.000000,0.000000
XS GIS Cut Line= 6
506569.968415632749451.446948386506434.107117094749469.901241081
 506168.64448061749501.393782603506072.143139714749515.664349412
505933.735008596 749535.17336006505575.960213929 749576.99096775
#Sta/Elev= 30
9499.015593.31299544.396573.19919584.764565.69589766.136511.85769816.487 489.351
9846.697470.78729866.837469.99229897.048460.82289917.239 448.7219937.455428.3266
9947.562421.33699967.778413.12999987.993 409.27910028.41412.611410038.51414.6802
10058.71423.308310068.81 428.266   10089446.4384 10129.4475.388410199.91516.9861
10240.18534.027110260.32545.213410310.66 548.91110320.73552.554410340.86565.7654
10371.07589.200810401.27601.735910411.34604.096210441.54626.517410500.99652.1783
#Mann= 3 , 0 , 0
9499.015    0.06       09499.015    0.06       010500.99    0.06       0
#XS Ineff= 2 , 0
       0                               0
Bank Sta=9499.015,10500.99
Exp/Cntr=0.3,0.1